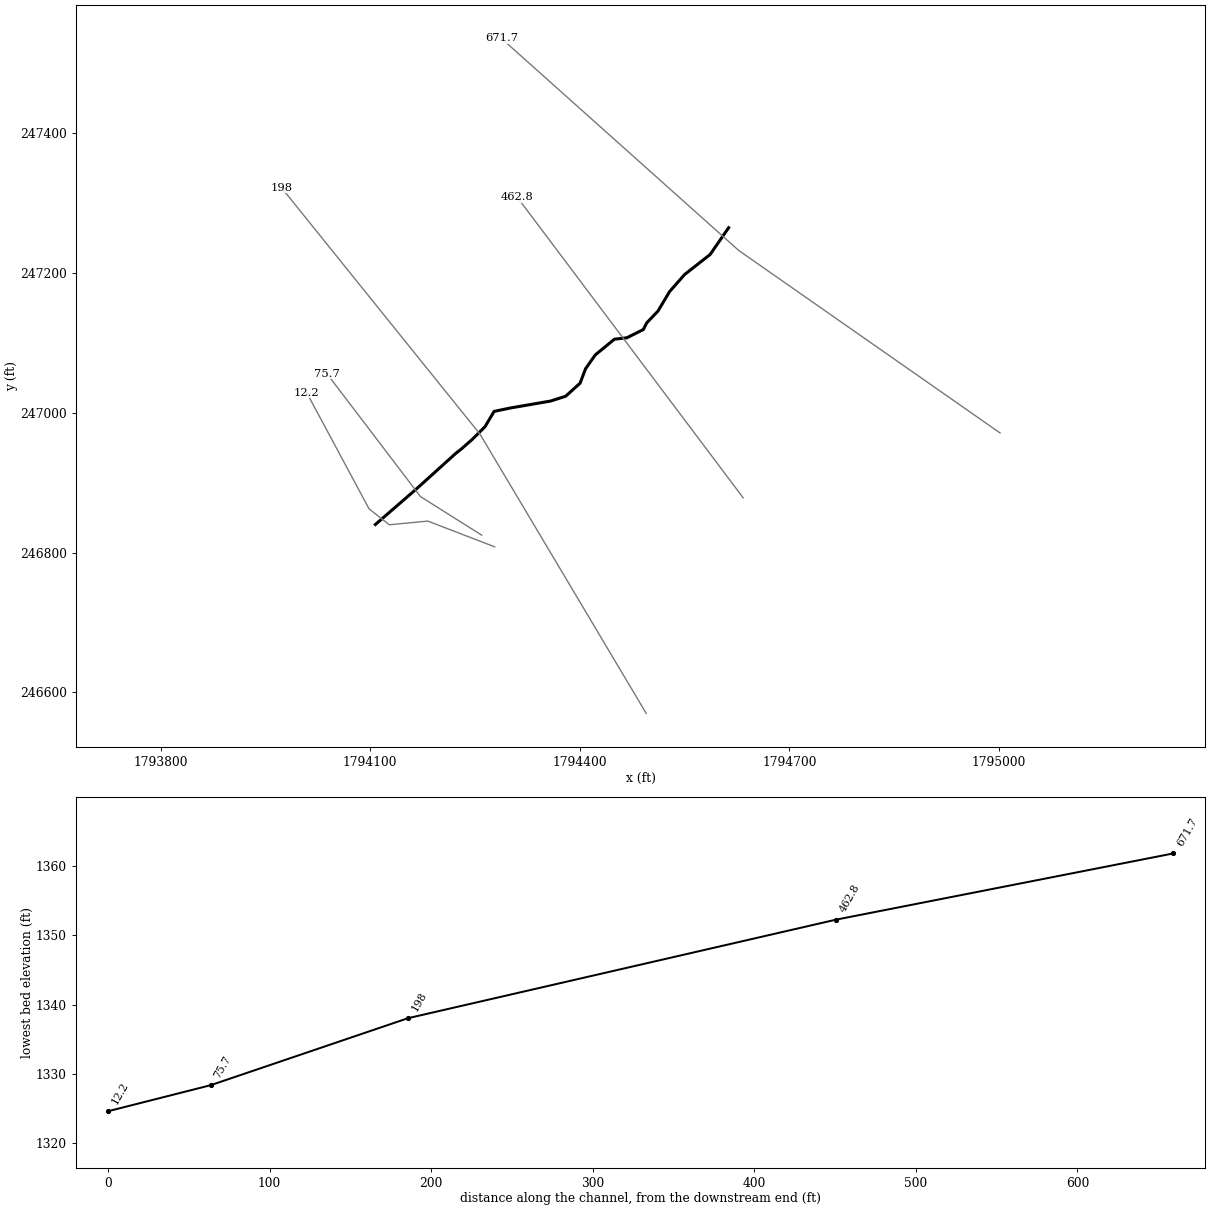
--- NP1027.prj (project) ---

Proj Title=NP1027
Current Plan=p01
Default Exp/Contr=0,0
English Units
Geom File=g01
Flow File=f01
Plan File=p01
BEGIN DESCRIPTION:
END DESCRIPTION:
DSS Export Rating Curves= 0
DSS Export Rating Curve Sorted= 0
DSS Export Volume Flow Curves= 0
DXF OffsetX= 0
DXF OffsetY= 0
DXF ScaleX= 0
DXF ScaleY= 0

--- NP1027.p01 (plan) ---

Plan Title=Floodplain
Program Version=4.00
Geom File=g01
Flow File=f01
K Sum by GR=0
Std Step Tol=0.01
Critical Tol=0.01
Num of Std Step Trials=20
Max Error Tol=0.3
Flow Tol Ratio=0.001
Split Flow NTrial=30
Split Flow Tol=0.02
Split Flow Ratio=0.02
Log Output Level=0
Friction Slope Method=1
Unsteady Friction Slope Method=2
Unsteady Bridges Friction Slope Method=1
Global Log Level=0
CheckData=False
Run HTab=0
Run UNet=0
Run PostProcess=0
UNET Theta=0
UNET Theta Warmup=0
UNET ZTol=0
UNET ZSATol=0
UNET MxIter=0
UNET MaxInSteps=0
UNET DtIC=0
UNET DtMin=0
UNET MaxCRTS=0
UNET WFStab=0
UNET SFStab=0
UNET WFX=0
UNET SFX=0
UNET DSS MLevel=0
UNET DZMax Abort=0
UNET Convert EG Bridges=0
UNET Use Existing IB Tables=0
UNET Froude Limit=0
UNET Froude Power=0
Write IC File=0
Echo Input=False
Echo Output=False
Write Detailed=0

--- NP1027.f01 (steady flow) ---

Flow Title=NFF Regression Equation
Program Version=4.00
Number of Profiles=1
Profile Names=P100yr
River Rch & RM=NP1027,Main      ,671.7
427.0725
River Rch & RM=NP1027,Main      ,462.8
574.6509
River Rch & RM=NP1027,Main      ,198
576.4209
Boundary for River Rch & Prof#=NP1027,Main      ,1
Up Type=0
Dn Type=3
Dn Slope=0.065402

--- NP1027.g01 (geometry) ---

Geom Title=USGS 10m DEM
Program Version=4.00

River Reach=NP1027          ,Main
Reach XY= 24
     1794612.944      247264.883      1794586.37      247226.499
     1794549.954      247197.957     1794528.302      247173.352
     1794511.842      247145.637     1794495.605      247128.627
     1794490.902       247119.22     1794467.281      247107.409
     1794449.565      247105.441     1794422.007      247082.804
     1794408.228       247063.12     1794400.355      247042.452
     1794379.686      247023.752     1794358.034      247016.862
     1794316.948      247009.779     1794300.949       247007.02
     1794277.328      247002.099     1794264.533      246980.446
     1794246.818      246962.731     1794234.855      246952.176
     1794230.086      246947.967     1794222.856      246942.344
     1794165.125        246890.2     1794107.432      246840.239

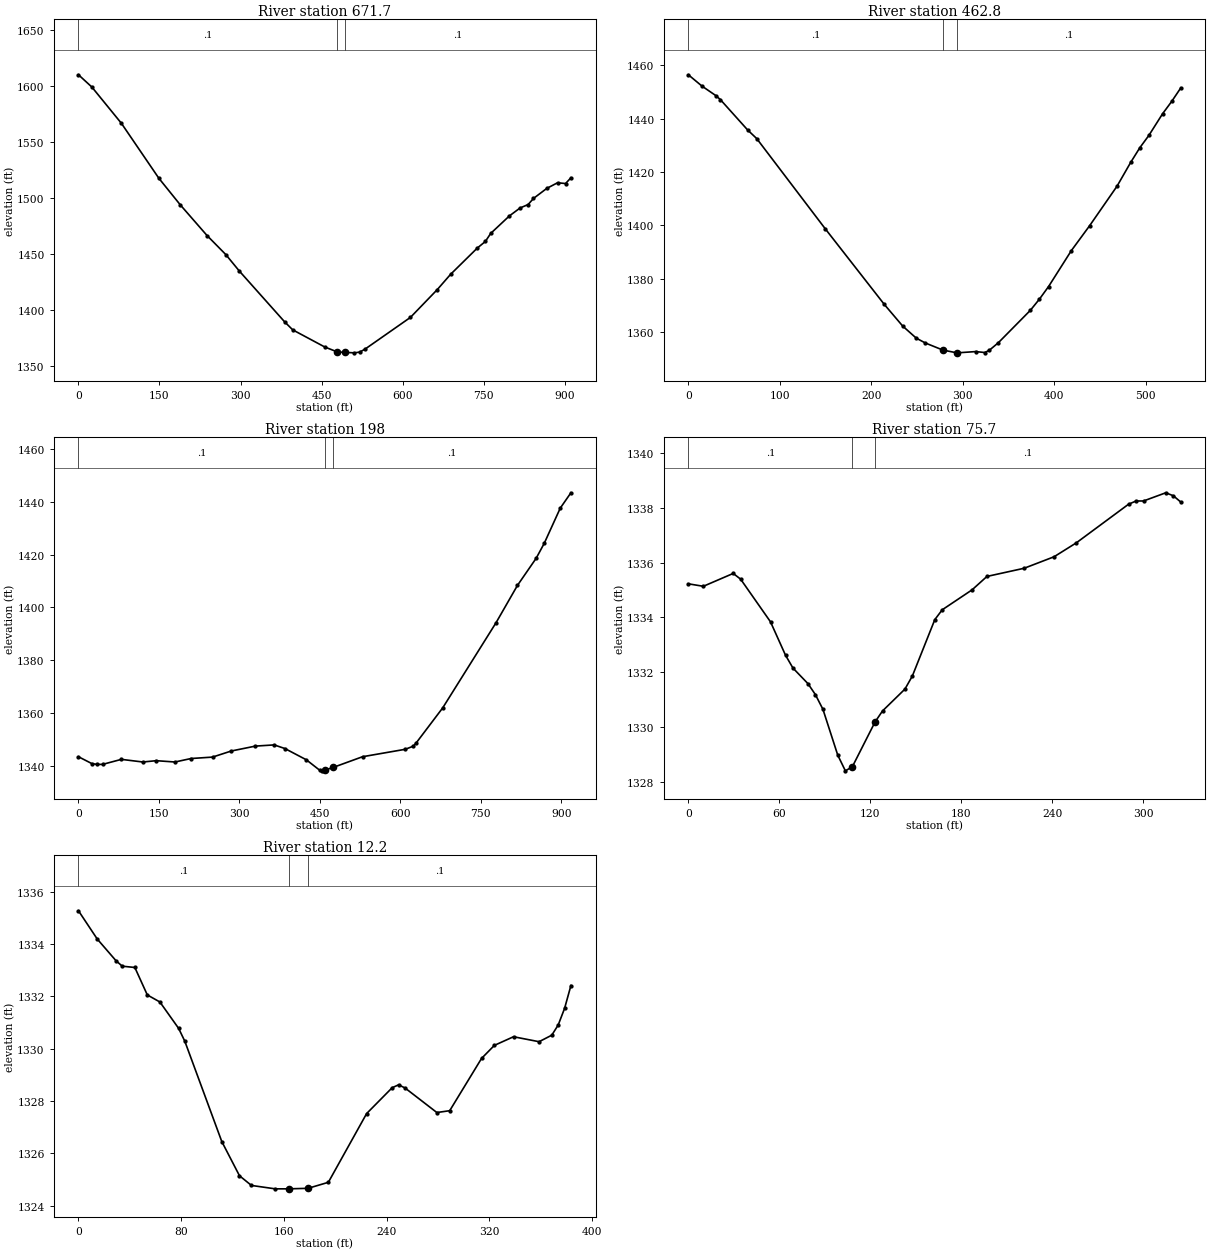
Type RM Length L Ch R = 1 ,671.7   ,213.1,208.9,205.2
XS GIS Cut Line= 3
     1795001.364      246971.213     1794627.303       247232.43
     1794287.706      247535.909
#Sta/Elev= 30
       0 1610.18    24.8 1599.22    79.4 1566.88   148.8 1517.76   188.4 1494.04
     238  1466.6   272.8 1449.56   297.6 1434.98   381.8 1389.42   396.7 1382.32
   456.2 1366.97   479.3  1362.6   494.3 1362.18   510.7  1361.8   520.6 1362.46
   530.5 1365.11   614.6 1393.47   664.2 1418.25   688.9 1431.92   738.4 1455.41
   753.3 1461.28   763.2 1468.47   797.8 1484.11   817.6 1491.21   832.5 1494.28
   842.4 1499.72   867.1 1508.72   886.9 1513.71   901.8 1513.04   911.7 1518.19
#Mann= 3 , 0 , 0
       0      .1       0   479.3    .045       0   494.3      .1       0
Bank Sta=479.3,494.3
XS Rating Curve= 0 ,0
Exp/Cntr=0.3,0.1

Type RM Length L Ch R = 1 ,462.8   ,266.6,264.9,265.6
XS GIS Cut Line= 2
     1794633.732      246878.418     1794310.441      247308.596
#Sta/Elev= 30
       0 1456.47      15  1452.2    29.9  1448.7    34.9  1447.2    64.8 1435.78
    74.7 1432.56   149.5 1398.79   214.2 1370.37   234.2 1362.29   249.1 1357.74
   259.1 1355.92   278.2 1353.28   293.2 1352.27     294 1352.25   313.9 1352.72
   323.9 1352.37   328.8 1353.19   338.8 1356.06   373.7 1368.18   383.7 1372.41
   393.6 1377.09   418.5 1390.56   438.5 1399.91   468.4  1414.7   483.3  1423.6
   493.3 1429.11   503.2 1433.73   518.2 1441.86   528.2  1446.5   538.1 1451.56
#Mann= 3 , 0 , 0
       0      .1       0   278.2    .045       0   293.2      .1       0
Bank Sta=278.2,293.2
XS Rating Curve= 0 ,0
Exp/Cntr=0.3,0.1

Type RM Length L Ch R = 1 ,198     ,116.1,122.2,121.6
XS GIS Cut Line= 3
     1794494.995      246569.983      1794257.23      246969.402
     1793972.937      247322.427
#Sta/Elev= 30
       0 1343.39      25 1340.79      35 1340.48      45  1340.5      80  1342.4
     120  1341.4     145  1341.9   179.9  1341.4   209.9 1342.72   249.9 1343.26
   284.9 1345.57   329.9 1347.43   364.9 1347.88   384.9  1346.5   424.8 1342.24
   449.8 1338.27   454.8 1338.05     460 1338.37     475 1339.36   529.6  1343.4
   609.3 1346.22   624.2  1347.4   629.2 1348.52     679  1361.9   778.6 1394.24
   818.5 1408.38   853.3 1418.64   868.3 1424.28   898.2 1437.64   918.1 1443.47
#Mann= 3 , 0 , 0
       0      .1       0     460    .045       0     475      .1       0
Bank Sta=460,475
XS Rating Curve= 0 ,0
Exp/Cntr=0.3,0.1

Type RM Length L Ch R = 1 ,75.7    ,50.4,63.5,69.2
XS GIS Cut Line= 3
     1794259.626      246824.974     1794172.013       246880.17
     1794037.966      247056.272
#Sta/Elev= 30
       0 1335.23     9.9 1335.14    29.6 1335.61    34.5  1335.4    54.2 1333.84
    64.1 1332.62      69 1332.15    78.9 1331.58    83.8 1331.18    88.8 1330.64
    98.6 1328.96   103.6 1328.39   108.2 1328.54   123.2 1330.18   128.1 1330.58
   142.9 1331.38   147.8 1331.86   162.6 1333.92   167.5 1334.28   187.2 1335.01
     197  1335.5   221.6  1335.8   241.3 1336.22     256 1336.73   290.4 1338.14
   295.4 1338.26   300.3 1338.26     315 1338.56     320 1338.45   324.9 1338.22
#Mann= 3 , 0 , 0
       0      .1       0   108.2    .045       0   123.2      .1       0
Bank Sta=108.2,123.2
XS Rating Curve= 0 ,0
Exp/Cntr=0.3,0.1

Type RM Length L Ch R = 1 ,12.2    ,27.7,12.2,7.9
XS GIS Cut Line= 5
     1794278.024      246808.328     1794182.526      246845.125
      1794127.33      246839.869     1794098.418      246862.648
     1794009.053      247029.112
#Sta/Elev= 30
       0 1335.28    14.6  1334.2    29.2 1333.37    34.1 1333.16    43.9 1333.11
    53.6 1332.06    63.4 1331.79      78 1330.78    82.8 1330.29   111.6 1326.45
   125.4 1325.14   134.7 1324.77   153.2 1324.64   163.8 1324.64   178.8 1324.66
   194.6 1324.89   224.4 1327.52   244.3 1328.51   249.3 1328.62   254.3  1328.5
   279.1 1327.56   289.1 1327.63   313.9 1329.63   323.9 1330.13   338.8 1330.46
   358.7 1330.27   368.6 1330.52   373.6 1330.91   378.6 1331.55   383.5 1332.42
#Mann= 3 , 0 , 0
       0      .1       0   163.8    .045       0   178.8      .1       0
Bank Sta=163.8,178.8
XS Rating Curve= 0 ,0
Exp/Cntr=0.3,0.1

Chan Stop Cuts=-1
Use User Specified Reach Order=0